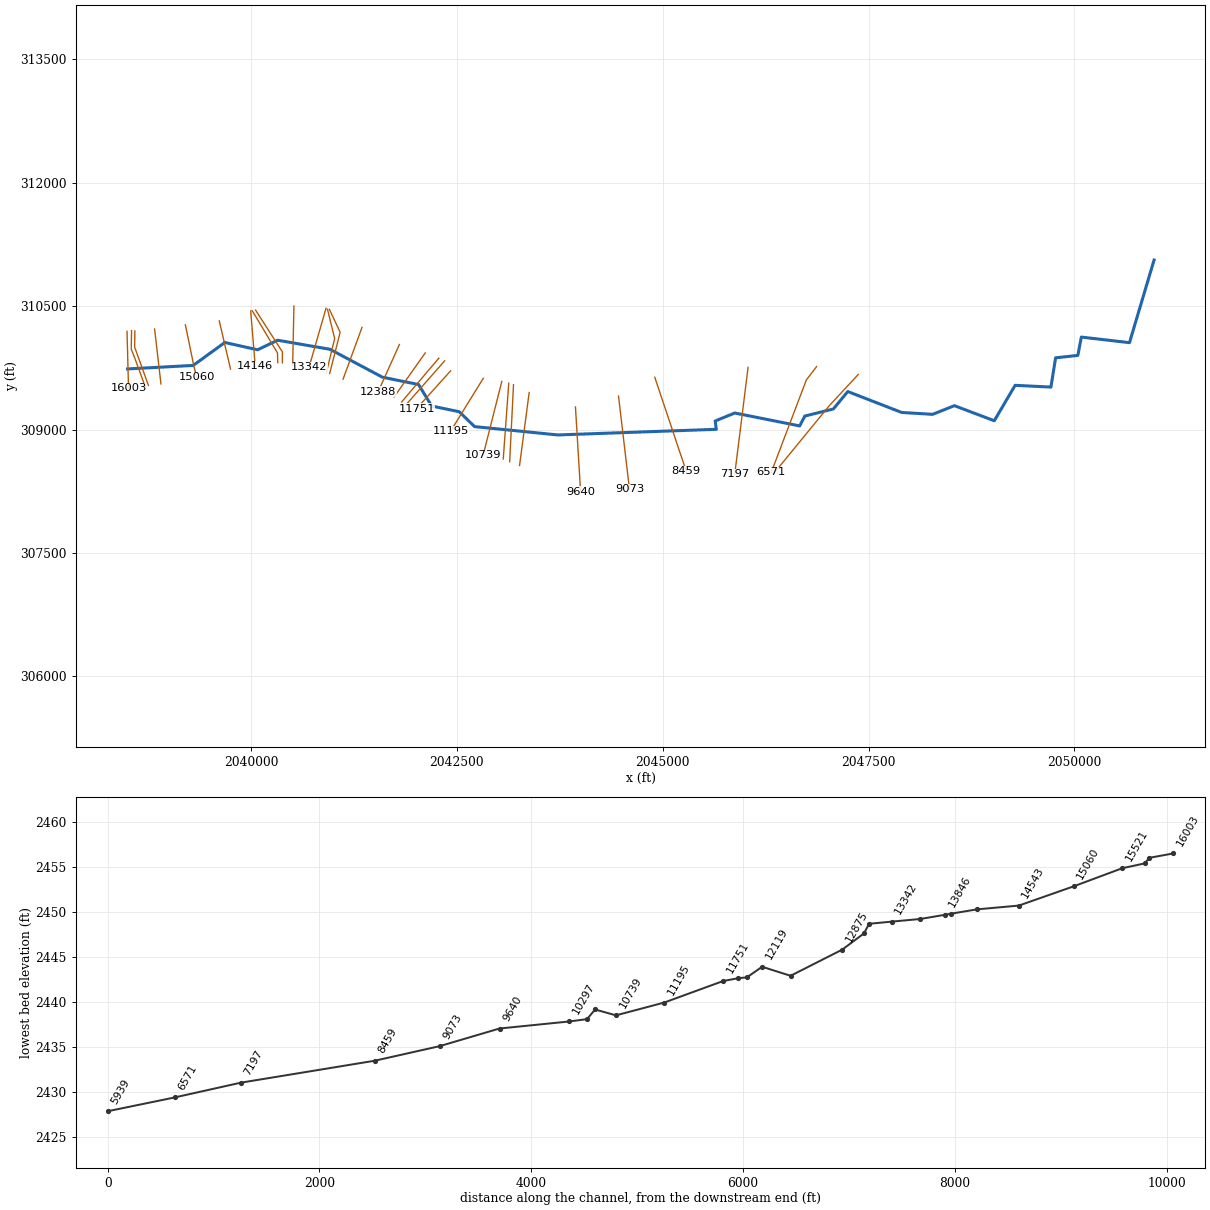
--- MORRISFK.prj (project) ---

Proj Title=MORRISFK
Current Plan=p01
Default Exp/Contr=0.3,0.1
English Units
Geom File=g02
Flow File=f01
Plan File=p01
Y Axis Title=Elevation
X Axis Title(PF)=Main Channel Distance
X Axis Title(XS)=Station
BEGIN DESCRIPTION:
Stream Name- Morris Fork
Flood Zone: Zone A
Greenbrier County, WV
County-Wide Study
WVDHSEM-2018-3, Flood Risk Project
HEC-RAS Version: 5.0.7
General Notes:
For the Hydrology regression was used.
END DESCRIPTION:
DSS File=dss
DSS Export Rating Curves= 0
DSS Export Rating Curve Sorted= 0
DSS Export Volume Flow Curves= 0
DXF Filename=..\H2c.
DXF OffsetX= 0
DXF OffsetY= 0
DXF ScaleX= 1
DXF ScaleY= 10

--- MORRISFK.p01 (plan) ---

Plan Title=Floodplain
Program Version=5.07
Short Identifier=Floodplain
Geom File=g02
Flow File=f01
Subcritical Flow
K Sum by GR= 0
Std Step Tol= 0.01
Critical Tol= 0.01
Num of Std Step Trials= 20
Max Error Tol= 0.3
Flow Tol Ratio= 0.001
Split Flow NTrial= 30
Split Flow Tol= 0.02
Split Flow Ratio= 0.02
Log Output Level= 0
Friction Slope Method= 1
Unsteady Friction Slope Method= 2
Unsteady Bridges Friction Slope Method= 1
Parabolic Critical Depth
Global Vel Dist= 0 , 0 , 0
Global Log Level= 0
CheckData=True
Encroach Param=-1 ,0,0, 0
Computation Interval=1MIN
Output Interval=1HOUR
Instantaneous Interval=1HOUR
Mapping Interval=1HOUR
Computation Time Step Use Courant=        0
Computation Time Step Use Time Series=    0
Computation Time Step Count To Double=0
Computation Time Step Max Doubling=0
Computation Time Step Max Halving=0
Computation Time Step Residence Courant=0
Run HTab= 0
Run UNet= 0
Run Sediment= 0
Run PostProcess= 0
Run WQNet= 0
Run RASMapper=-1
UNET Theta= 1
UNET Theta Warmup= 1
UNET ZTol= 0.02
UNET ZSATol= 0.02
UNET MxIter= 20
UNET Max Iter WO Improvement= 0
UNET MaxInSteps= 0
UNET DtIC= 0
UNET DtMin= 0
UNET MaxCRTS= 20
UNET WFStab= 2
UNET SFStab= 1
UNET WFX= 1
UNET SFX= 1
UNET 1D Methodology=Finite Difference
UNET DSS MLevel= 4
UNET Pardiso=0
UNET DZMax Abort= 100
UNET Use Existing IB Tables=-1
UNET Froude Reduction=False
UNET Froude Limit= 0.8
UNET Froude Power= 4
UNET D1 Cores= 0
UNET D2 Coriolis=0
UNET D2 Cores= 0
UNET D2 Theta= 1
UNET D2 Theta Warmup= 1
UNET D2 Z Tol= 0.01
UNET D2 Volume Tol= 0.01
UNET D2 Max Iterations= 20
UNET D2 Equation= 0
UNET D2 RampUpFraction=0.1
UNET D2 TimeSlices= 1
UNET D2 BCVolumeCheck=0
UNET D1D2 MaxIter= 0
UNET D1D2 ZTol=0.01
UNET D1D2 QTol=0.1
UNET D1D2 MinQTol=1
DSS File=dss
Write IC File= 0
Write IC File at Fixed DateTime=0
Write IC File at Sim End=0
Echo Input=False
Echo Parameters=False
Echo Output=False
Write Detailed= 0
HDF Write Warmup=0
HDF Write Time Slices=0
HDF Flush=0
HDF Face Node Velocities=0
HDF Compression= 1
HDF Chunk Size= 1
HDF Spatial Parts= 1
HDF Use Max Rows=0
HDF Fixed Rows= 1
Calibration Method= 0
Calibration Iterations= 20
Calibration Max Change=0.05
Calibration Tolerance=0.2
Calibration Maximum=1.5
Calibration Minimum=0.5
Calibration Optimization Method= 1
WQ AD Non Conservative
WQ ULTIMATE=-1
WQ Max Comp Step=1HOUR
WQ Output Interval=15MIN
WQ Output Selected Increments= 0
WQ Output face flow=0
WQ Output face velocity=0
WQ Output face area=0
WQ Output face dispersion=0
WQ Output cell volume=0
WQ Output cell surface area=0
WQ Output cell continuity=0
WQ Output cumulative cell continuity=0
WQ Output face conc=0
WQ Output face dconc_dx=0
WQ Output face courant=0
WQ Output face peclet=0
WQ Output face adv mass=0
WQ Output face disp mass=0
WQ Output cell mass=0
WQ Output cell source sink temp=0
WQ Output nsm pathways=0
WQ Output nsm derived pathways=0
WQ Output MaxMinRange=-1
WQ Daily Max Min Mean=-1
WQ Daily Range=0
WQ Daily Time=0
WQ Create Restart=0
WQ Fixed Restart=0
WQ System Summary=0
WQ Write To DSS=0
WQ Use Fixed Temperature=0
Sorting and Armoring Iterations= 10
XS Update Threshold= 0.02
Bed Roughness Predictor= 0
Hydraulics Update Threshold= 0.02
Energy Slope Method= 1
Volume Change Method= 1
Sediment Retention Method= 0
XS Weighting Method= 0
Number of US Weighted Cross Sections= 1
Number of DS Weighted Cross Sections= 1
Upstream XS Weight=0
Main XS Weight=1
Downstream XS Weight=0
Number of DS XS's Weighted with US Boundary= 1
Upstream Boundary Weight= 1
Weight of XSs Associated with US Boundary= 0
Number of US XS's Weighted with DS Boundary= 1
Downstream Boundary Weight= 0.5
Weight of XSs Associated with DS Boundary= 0.5
Percentile Method= 0
Sediment Output Level= 3
Mass or Volume Output= 0
Output Increment Type= 1
Profile and TS Output Increment= 1
XS Output Flag= 0
XS Output Increment= 10
Write Gradation File= 0
Read Gradation Hotstart= 0
Write HDF5 File= 1
Write Binary Output= 1
Write DSS Sediment File= 0
SV Curve= 0
Specific Gage Flag= 0

--- MORRISFK.f01 (steady flow) ---

Flow Title=H2c
Program Version=5.07
Number of Profiles= 6
Profile Names=f1p,f10p,f4p,f2p,f02p,f1pplus
River Rch & RM=MORRISFK,Main            ,16003
     515     271     361     436     721     762
River Rch & RM=MORRISFK,Main            ,15521
     599     317     421     507     836     886
River Rch & RM=MORRISFK,Main            ,12119
     676     360     477     573     942    1000
River Rch & RM=MORRISFK,Main            ,7197
     752     402     532     638    1050    1110
River Rch & RM=MORRISFK,Main            ,5358
     836     448     592     710    1160    1240
Boundary for River Rch & Prof#=MORRISFK,Main            , 1
Up Type= 0
Dn Type= 3
Dn Slope=0.00185
Boundary for River Rch & Prof#=MORRISFK,Main            , 2
Up Type= 0
Dn Type= 3
Dn Slope=0.00185
Boundary for River Rch & Prof#=MORRISFK,Main            , 3
Up Type= 0
Dn Type= 3
Dn Slope=0.00185
Boundary for River Rch & Prof#=MORRISFK,Main            , 4
Up Type= 0
Dn Type= 3
Dn Slope=0.00185
Boundary for River Rch & Prof#=MORRISFK,Main            , 5
Up Type= 0
Dn Type= 3
Dn Slope=0.00185
Boundary for River Rch & Prof#=MORRISFK,Main            , 6
Up Type= 0
Dn Type= 3
Dn Slope=0.00185
DSS Import GetInterval= 0
DSS Import GetPeak= 0
DSS Import FillOption= 0

--- MORRISFK.g02 (geometry) ---

Geom Title=MorrisFork
Program Version=5.07

River Reach=MORRISFK        ,Main
Reach XY= 30
     2038502.132      309737.813     2039298.898       309780.29
2039683.35285831310059.3636334132040080.34185097309970.412632146
 2040323.8026085310086.7218300592040958.31743914309976.942973434
     2041596.377       309637.542042035.78482188309548.287622343
2042194.42802494309287.1370582662042530.11141256309217.639491253
2042715.73882245309036.8979549772043725.25850828 308935.51385831
2045652.04903612309004.082786747 2045637.8523662309105.129919827
 2045874.7381831309202.072592633  2046664.153705309045.252497375
2046726.06341647309164.7666296862047073.00939144309251.393632777
2047248.10532604 309463.089116072047902.30935303309208.872369142
2048278.30771338309186.029664237     2048542.619      309291.256
      2049027.37      309108.1632049279.94389631309538.498343785
2049715.14911116309517.2303703142049771.99452907309873.054762864
2050041.80707004309902.1078821572050084.45560977310124.940193318
     2050669.007      310056.966     2050967.511      311061.039

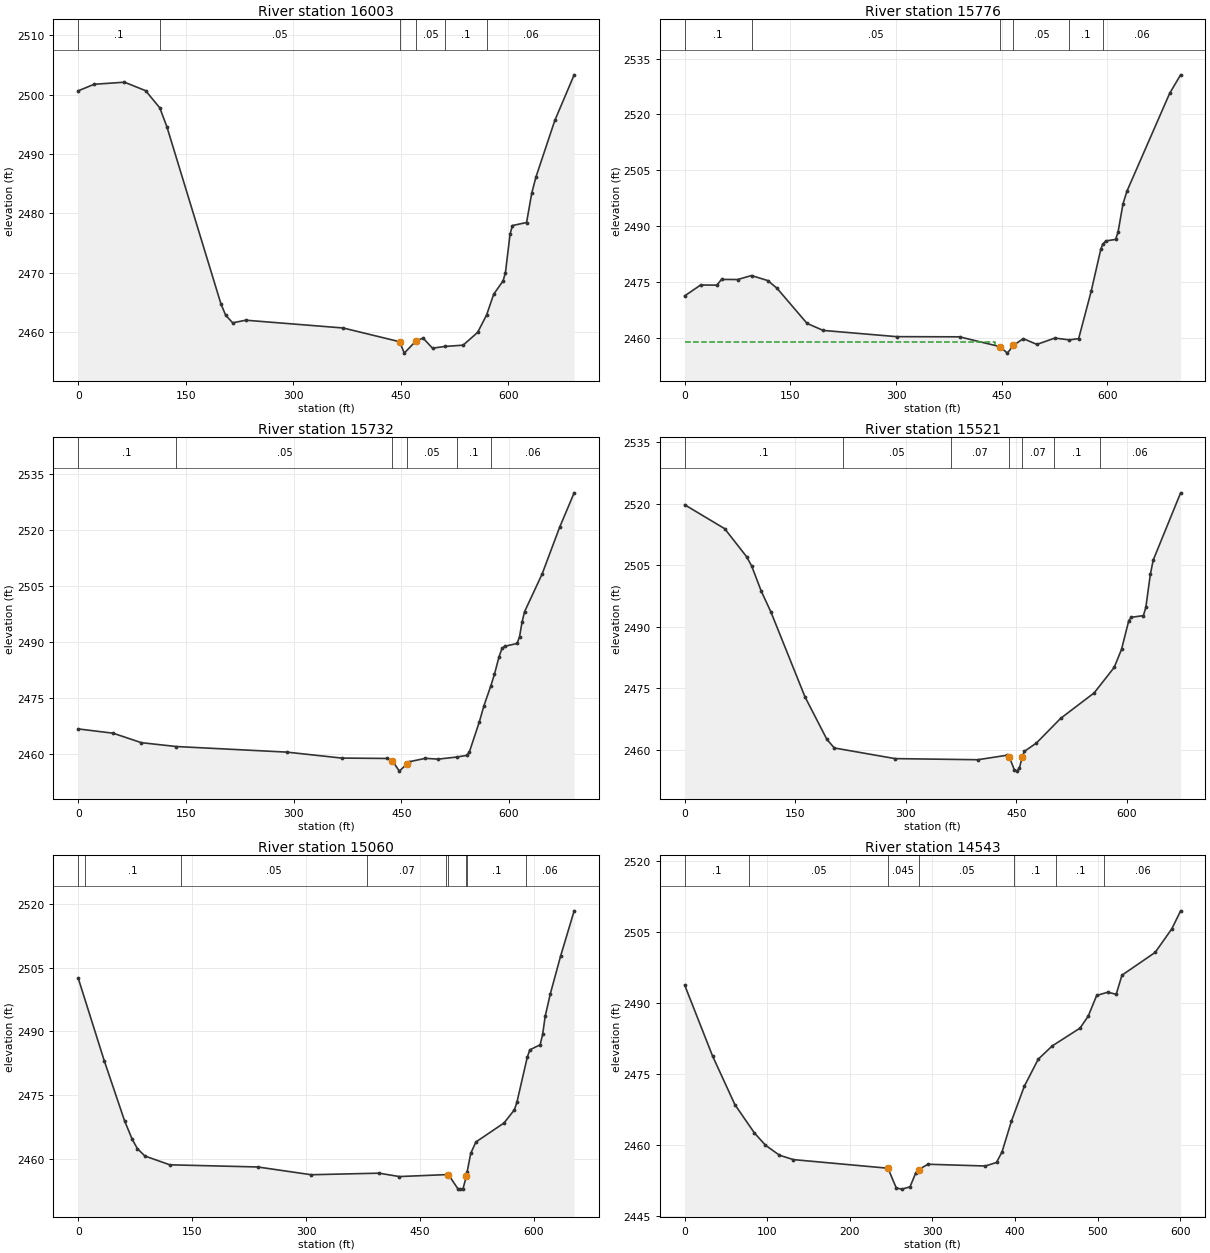
Type RM Length L Ch R = 1 ,16003   ,216.9,227.4,223.6
XS GIS Cut Line= 2
2038495.19826495310195.219755001 2038513.4736061309503.265128038
#Sta/Elev= 30
       0 2500.63    22.3 2501.73    64.6 2502.08    94.1 2500.65   113.8 2497.77
   123.7 2494.61   199.1 2464.82   205.7 2462.89   215.6 2461.59   233.9 2462.03
   369.8 2460.72   448.6 2458.41   455.1 2456.49   471.5 2458.55   481.4 2459.02
   494.5 2457.32   511.5 2457.61   537.2 2457.83   557.5 2459.98     570 2462.91
   579.9  2466.4     593 2468.65   596.3 2470.05   602.8 2476.55   606.1 2477.96
   625.8 2478.47     633 2483.41   638.9 2486.13   665.2 2495.64   692.2 2503.32
#Mann= 6 ,-1 , 0
       0      .1       0   113.8     .05       0   448.6    .045       0
   471.5     .05       0   511.5      .1       0     570     .06       0
Bank Sta=448.6,471.5
XS Rating Curve= 0 ,0
Exp/Cntr(USF)=0,0
Exp/Cntr=0.5,0.3

Type RM Length L Ch R = 1 ,15776   ,44.1,44,44.4
XS GIS Cut Line= 4
2038550.14590715310202.5885419012038546.48431954309978.011168494
2038594.08495847309857.1787773672038713.69682039309528.856421679
#Sta/Elev= 30
       0 2471.35    22.7 2474.28    45.7 2474.23    52.3 2475.77    75.2 2475.74
    94.9 2476.81   117.9 2475.46     131 2473.41   173.7 2463.97   196.6 2462.09
   300.8 2460.42   390.1 2460.37   447.5 2457.74     458    2456   466.6 2458.07
   480.6 2459.89   499.9 2458.34   525.4 2460.04   545.9 2459.55   559.2 2459.89
   576.9 2472.55   590.7 2483.93   593.3 2485.17   597.7 2486.09   611.6  2486.5
   615.1 2488.46   622.1 2496.03   627.8 2499.48   688.4  2525.7   703.9 2530.64
#Mann= 6 ,-1 , 0
       0      .1       0    94.9     .05       0   447.5    .045       0
   466.6     .05       0   545.9      .1       0   593.3     .06       0
#XS Ineff= 2 , 0
          439.85    2459  475.35            2459
Permanent Ineff=
       F       F
Bank Sta=447.5,466.6
XS Rating Curve= 0 ,0
Exp/Cntr(USF)=0,0
Exp/Cntr=0.5,0.3

Type RM Length L Ch R = 1 ,15732   ,213,211,208.2
XS GIS Cut Line= 3
2038590.42337086310198.9269542912038587.98231245 310002.42175256
 2038755.1948133309537.400126102
#Sta/Elev= 30
       0  2466.7    48.6 2465.55      88 2463.01   136.5 2461.98   290.4 2460.48
   367.1 2458.88   429.8 2458.78   437.72458.118   447.2 2455.38     4582457.325
   461.2 2457.91   483.6 2458.81   501.5  2458.6     528 2459.18   541.4 2459.62
   544.9  2460.6   558.8 2468.69   565.1 2472.94   574.8 2478.34   579.7 2481.35
   586.1 2486.08   590.2 2488.27   593.8 2488.85   611.1 2489.61   614.6 2491.37
   618.1  2495.3   621.6 2498.13     646 2508.21   670.4 2520.75   690.7 2530.02
#Mann= 6 ,-1 , 0
       0      .1       0   136.5     .05       0   437.7    .045       0
     458     .05       0     528      .1       0   574.8     .06       0
Bank Sta=437.7,458
XS Rating Curve= 0 ,0
Exp/Cntr(USF)=0,0
Exp/Cntr=0.5,0.3

Type RM Length L Ch R = 1 ,15521   ,453.2,461.3,457.7
XS GIS Cut Line= 2
2038830.04972941310224.005304509 2038907.2632664309555.556684305
#Sta/Elev= 30
       0 2519.78    54.3 2513.95    84.1  2507.1    90.9 2504.85   103.9 2498.73
   117.1  2493.6   163.3 2472.93     193 2462.58     203  2460.5   285.5  2457.9
   397.8 2457.63   437.4 2458.73   440.7 2458.21   447.3 2455.16   450.7 2454.85
     454 2455.51     458 2458.31   460.9 2459.67   477.1 2461.67   510.1 2467.71
   555.7 2473.94   582.8 2480.14   592.7 2484.53   602.6 2491.56     606 2492.35
   622.4 2492.76   625.7 2494.77   631.8 2502.79   635.7 2506.29   672.9 2522.69
#Mann= 7 ,-1 , 0
       0      .1       0  215.41     .05       0  360.88     .07       0
   440.7    .045       0     458     .07       0  500.94      .1       0
  563.23     .06       0
Bank Sta=440.7,458
XS Rating Curve= 0 ,0
Exp/Cntr(USF)=0,0
Exp/Cntr=0.3,0.1

Type RM Length L Ch R = 1 ,15060   ,503.3,516.6,505.9
XS GIS Cut Line= 3
     2039204.193      310272.467      2039305.18      309781.778
2039342.11286724309634.369137381
#Sta/Elev= 30
       0 2502.54    34.2 2483.12      61 2468.94    71.1 2464.56    77.8  2462.4
    87.8 2460.63   120.6 2458.56   236.3 2458.05   306.7 2456.22     396 2456.59
   422.8 2455.79   487.3 2456.27   499.8 2452.93   503.2 2452.83   506.6 2452.94
   511.1 2455.94     512 2456.85   516.7 2461.23   523.5 2463.93   560.6 2468.42
   574.3 2471.53   577.6 2473.34   591.1 2483.84   594.5 2485.64   608.1 2486.83
   611.4 2489.26   614.8 2493.58   621.6 2498.89   635.1 2507.75   652.9 2518.39
#Mann= 9 ,-1 , 0
       0      .1       0    8.78      .1       0  135.68     .05       0
  379.91     .07       0  484.02      .1       0   487.3    .045       0
   511.1      .1       0     512      .1       0  589.61     .06       0
Bank Sta=487.3,511.1
XS Rating Curve= 0 ,0
Exp/Cntr=0.3,0.1

Type RM Length L Ch R = 1 ,14543   ,395.7,396.7,388.5
XS GIS Cut Line= 2
2039615.42170562310321.0737510082039752.19997115309736.456970961
#Sta/Elev= 30
       0 2493.75    33.8 2478.77    60.8 2468.53    84.4 2462.56    97.8 2459.97
   114.7 2457.86   131.5 2456.93   246.1 2455.11   256.2 2450.93   262.9  2450.7
   272.8 2451.18   279.8 2454.15   283.2 2454.83   294.6 2455.95     364 2455.58
   377.5 2456.32   384.2 2458.57   395.6 2465.06   411.2 2472.42     428 2478.11
   444.9 2480.91   478.6 2484.67   488.5 2487.19   498.8 2491.57   512.3 2492.25
   522.4 2491.81   529.4 2495.84   569.6 2500.65   589.8 2505.64   600.4 2509.42
#Mann= 7 ,-1 , 0
       0      .1       0   78.22     .05       0   246.1    .045       0
   283.2     .05       0  398.89      .1       0  450.13      .1       0
  507.75     .06       0
Bank Sta=246.1,283.2
XS Rating Curve= 0 ,0
Exp/Cntr(USF)=0,0
Exp/Cntr=0.3,0.1

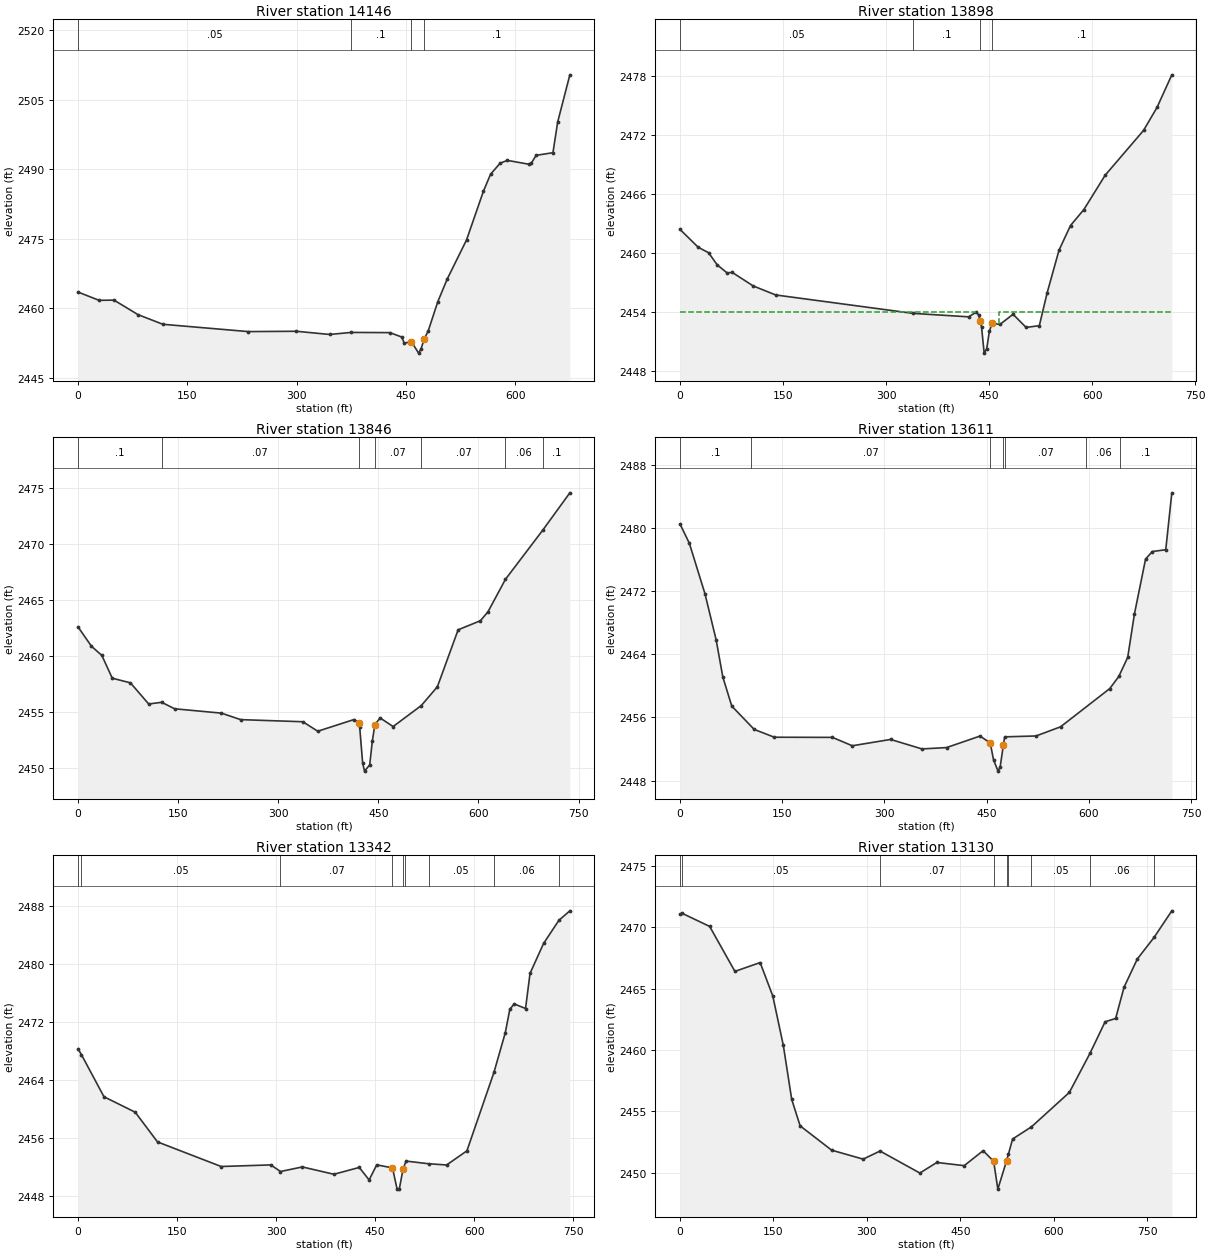
Type RM Length L Ch R = 1 ,14146   ,241.3,248,249.2
XS GIS Cut Line= 2
2039997.07718845310442.4093091312040052.22971487309769.548486813
#Sta/Elev= 30
       0 2463.47      29 2461.68    49.4 2461.73    82.4 2458.59   116.5 2456.51
   233.8 2454.93   299.8    2455   345.5 2454.31   374.7 2454.75     428 2454.71
   444.5 2453.75   447.8 2452.42   457.6 2452.76   467.5 2450.28   470.8 2451.18
   475.1  2453.3   480.7 2455.08   493.8 2461.37   506.7 2466.26   533.3 2474.73
   556.4 2485.22   566.3 2488.93   579.4  2491.3   589.3 2491.91   618.9 2491.08
   622.2 2491.31   628.8    2493   651.9 2493.57   658.4 2500.21   675.1 2510.39
#Mann= 4 ,-1 , 0
       0     .05       0   374.7      .1       0   457.6    .045       0
   475.1      .1       0
Bank Sta=457.6,475.1
XS Rating Curve= 0 ,0
Exp/Cntr(USF)=0,0
Exp/Cntr=0.5,0.3

Type RM Length L Ch R = 1 ,13898   ,52.3,52.9,53.2
XS GIS Cut Line= 3
2040015.97500208310445.3105952562040322.65817356 309931.66914075
2040325.78909868 309813.85116116
#Sta/Elev= 30
       0 2462.41    26.4 2460.59    41.7 2460.02    54.2 2458.79    68.6 2457.97
    76.1 2458.02   106.6 2456.64   139.3 2455.72   339.7 2453.84   420.3 2453.49
   431.4 2453.98   435.3 2453.64   437.1 2453.03   439.1 2452.45   442.9 2449.79
   446.6 2450.24   450.5 2452.02   454.4 2452.84   465.8 2452.71   484.9 2453.75
     504 2452.41   523.2 2452.59   534.6 2455.94   551.9 2460.29   568.6  2462.8
   588.1 2464.43   619.1 2467.93   674.9 2472.49   694.6 2474.84   716.1 2478.16
#Mann= 4 ,-1 , 0
       0     .05       0   339.7      .1       0   437.1    .045       0
   454.4      .1       0
#XS Ineff= 2 , 0
          430.55    2454  464.29            2454
Permanent Ineff=
       F       F
Bank Sta=437.1,454.4
XS Rating Curve= 0 ,0
Exp/Cntr(USF)=0,0
Exp/Cntr=0.5,0.3

Type RM Length L Ch R = 1 ,13846   ,242.1,234.3,227.9
XS GIS Cut Line= 3
2040056.42579971310452.7214777192040381.84641276309945.143111157
2040381.99827338  309811.0496888
#Sta/Elev= 30
       0 2462.59    20.1 2460.86    35.7 2460.04    51.3    2458    78.6 2457.58
   105.9 2455.69   125.4 2455.84   144.8 2455.26     215 2454.87   243.6 2454.29
     337  2454.1   359.2 2453.25   413.7  2454.3   420.6 2454.01   422.1 2453.61
   426.5 2450.42   429.3 2449.68   437.1 2450.24     441 2452.37   444.9 2453.85
   452.7 2454.44   472.2 2453.67   514.4 2455.55   538.5 2457.23   569.6 2462.33
   602.9 2463.14   614.3 2463.94   640.5 2466.85   696.3 2471.24     737 2474.59
#Mann= 7 ,-1 , 0
       0      .1       0   125.4     .07       0   420.6    .045       0
   444.9     .07       0   514.4     .07       0   640.5     .06       0
   696.3      .1       0
Bank Sta=420.6,444.9
XS Rating Curve= 0 ,0
Exp/Cntr(USF)=0,0
Exp/Cntr=0.5,0.3

Type RM Length L Ch R = 1 ,13611   ,271.1,269.3,266.7
XS GIS Cut Line= 2
2040522.12923996310501.9740376642040506.68653256309780.578992097
#Sta/Elev= 30
       0 2480.49    13.7 2478.06    36.7 2471.65    53.1 2465.81    62.9 2461.11
      76 2457.44   108.9 2454.49   138.4  2453.5   223.7 2453.48   252.8 2452.42
     309 2453.22     355 2452.02   391.1 2452.19   440.3 2453.65   455.2 2452.77
     460 2450.66   466.6 2449.21   469.8 2449.77   474.5 2452.53   476.4 2453.55
   522.4 2453.66   558.4 2454.82   630.6 2459.66   643.8 2461.19   656.9 2463.61
   666.7 2469.08   683.1 2476.05     693    2477   712.7 2477.23   721.6 2484.43
#Mann= 7 ,-1 , 0
       0      .1       0  104.07     .07       0   455.2    .045       0
   474.5     .07       0   476.4     .07       0  596.01     .06       0
  646.18      .1       0
Bank Sta=455.2,474.5
XS Rating Curve= 0 ,0
Exp/Cntr(USF)=0,0
Exp/Cntr=0.3,0.1

Type RM Length L Ch R = 1 ,13342   ,211,212.4,212.2
XS GIS Cut Line= 2
 2040911.3493313310473.535149141  2040705.446566309757.777917385
#Sta/Elev= 30
       0 2468.27     5.1 2467.48    39.3 2461.66    86.6 2459.53   120.4 2455.43
   216.8 2452.04   291.9 2452.26   306.6 2451.35   339.7 2451.98   387.5 2450.97
   425.9 2451.91   440.8 2450.19   452.4 2452.27   476.2 2451.85   483.1 2448.96
   486.5 2448.92   492.2 2451.68   496.7 2452.79   530.9 2452.42   558.2 2452.25
   588.9  2454.2   629.9 2465.03     647 2470.48   653.9 2473.73   660.6 2474.46
   677.7 2473.83   684.5 2478.67     705  2482.8   728.2 2485.99   744.8  2487.3
#Mann= 9 ,-1 , 0
       0      .1       0     5.1     .05       0   306.6     .07       0
   476.2    .045       0   492.2     .07       0   494.6     .07       0
   530.9     .05       0   629.9     .06       0   728.2      .1       0
Bank Sta=476.2,492.2
XS Rating Curve= 0 ,0
Exp/Cntr(USF)=0,0
Exp/Cntr=0.5,0.3

Type RM Length L Ch R = 1 ,13130   ,48.1,48.8,49
XS GIS Cut Line= 3
2040929.88267447310462.4045551152041016.71033229310106.421599534
2040916.46350029309695.312735875
#Sta/Elev= 30
       0 2471.07     3.8 2471.12    47.7 2470.06    88.2  2466.4   128.7 2467.12
     149  2464.4   165.9 2460.38   179.4 2455.98   192.9 2453.83   243.5 2451.85
   294.1 2451.12   321.2 2451.78   385.1 2449.99   412.4 2450.85   456.3 2450.59
   486.7 2451.81   503.6 2450.94   510.3 2448.68   524.3 2450.98   527.2 2451.51
     534 2452.76   564.3 2453.75   625.1 2456.55   658.3 2459.74   682.5  2462.3
   699.4 2462.57   712.9 2465.11   734.2 2467.41     761 2469.16   789.6 2471.33
#Mann= 9 ,-1 , 0
       0      .1       0     3.8     .05       0   321.2     .07       0
   503.6    .045       0   524.3     .07       0   527.2     .07       0
   564.3     .05       0   658.3     .06       0     761      .1       0
Bank Sta=503.6,524.3
XS Rating Curve= 0 ,0
Exp/Cntr(USF)=0,0
Exp/Cntr=0.5,0.3

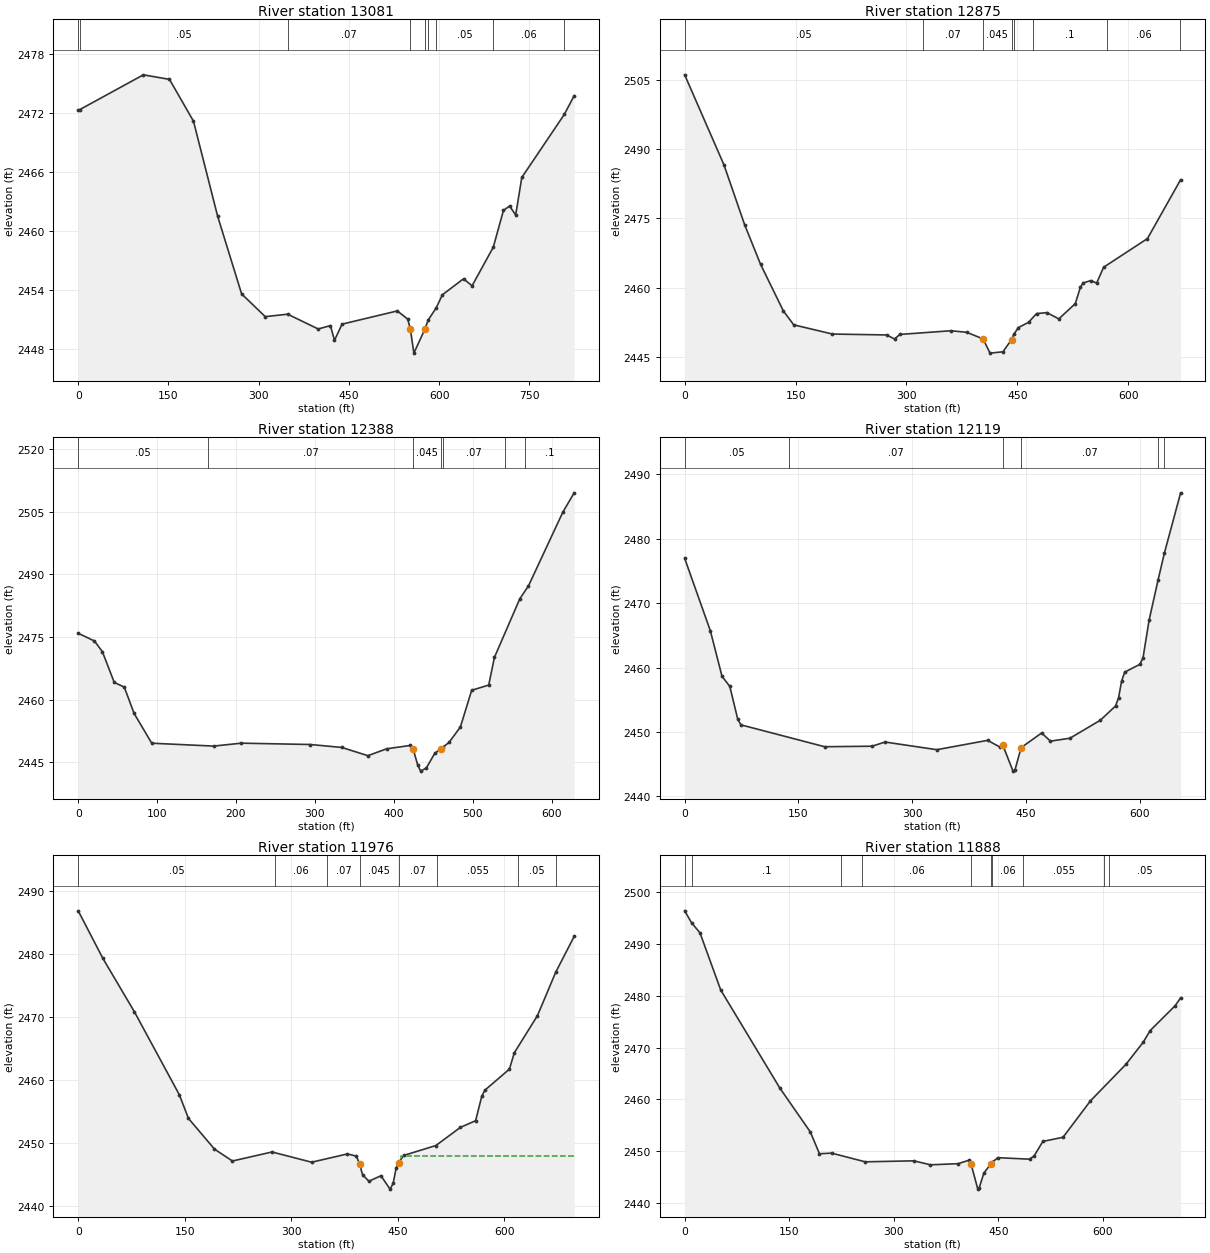
Type RM Length L Ch R = 1 ,13081   ,205.6,205.6,204
XS GIS Cut Line= 3
2040953.06295995310461.5766877762041083.45206577310184.034162524
 2040956.3798539309682.116089508
#Sta/Elev= 30
       0 2472.26     2.5 2472.31   108.3 2475.84   151.7 2475.38   191.6 2471.14
   231.8 2461.49   271.6 2453.62   310.9 2451.31   348.2 2451.56   398.9 2450.06
   419.2  2450.4     426 2448.91   438.6 2450.55   530.4 2451.89   547.8 2451.06
   552.1 2450.04     558 2447.61   576.4 2450.06   581.7 2450.95   595.3 2452.23
   605.4 2453.53   640.5 2455.15   654.7 2454.44     690 2458.36   706.9 2462.09
   717.1 2462.53   727.2 2461.62   737.4 2465.43   808.1 2471.83   824.4 2473.72
#Mann= 9 ,-1 , 0
       0      .1       0     2.5     .05       0   348.2     .07       0
   552.1    .045       0   576.4     .07       0   581.7     .07       0
   595.3     .05       0     690     .06       0   808.1      .1       0
Bank Sta=552.1,576.4
XS Rating Curve= 0 ,0
Exp/Cntr(USF)=0,0
Exp/Cntr=0.5,0.3

Type RM Length L Ch R = 1 ,12875   ,487.1,487.4,483.4
XS GIS Cut Line= 2
2041349.18190259310242.9582567812041118.76690332  309612.9938439
#Sta/Elev= 30
       0  2506.1    53.2 2486.57    81.1 2473.63   102.6 2465.06   133.5 2454.95
   147.5 2451.94   199.9 2449.94   273.3 2449.75   283.8 2448.87   291.1 2449.86
   360.2 2450.66   381.6 2450.32   403.7 2448.88     413 2445.81   430.5  2446.1
   442.1 2448.74   445.1 2449.87   451.4 2451.35   465.1 2452.48   475.9 2454.37
   489.9 2454.59     506 2453.23   528.3 2456.52   535.3  2460.1   538.8 2461.01
   549.5 2461.53   557.2 2460.98   566.7 2464.42   625.9 2470.62   670.8 2483.38
#Mann= 8 ,-1 , 0
       0     .05       0  322.62     .07       0   403.7    .045       0
   442.1     .07       0   445.1     .07       0  471.27      .1       0
  570.69     .06       0   670.1      .1       0
Bank Sta=403.7,442.1
XS Rating Curve= 0 ,0
Exp/Cntr(USF)=0,0
Exp/Cntr=0.3,0.1

Type RM Length L Ch R = 1 ,12388   ,265.9,268.7,264.3
XS GIS Cut Line= 2
2041802.65823092310034.604268085 2041545.2797743309461.017993322
#Sta/Elev= 30
       0 2475.89    20.6 2474.04    30.6  2471.5    45.7 2464.13    58.4 2463.01
    70.9  2456.7    93.2 2449.59   171.6  2448.9   206.9  2449.6   293.9 2449.28
     334 2448.58   367.2 2446.61     391 2448.25   420.8 2449.05   424.52448.263
   430.5 2444.29   434.1 2442.91   441.3 2443.66   452.1  2447.2   460.5 2448.28
   462.5 2448.67   470.1 2449.77   484.5 2453.48   498.8 2462.25   520.4  2463.5
   527.6 2470.11   559.8 2484.14   570.8 2487.23   614.4 2504.88   628.7 2509.49
#Mann= 7 ,-1 , 0
       0     .05       0  164.94     .07       0   424.5    .045       0
   460.5     .07       0   462.5     .07       0  540.46     .06       0
  566.54      .1       0
Bank Sta=424.5,460.5
XS Rating Curve= 0 ,0
Exp/Cntr(USF)=0,0
Exp/Cntr=0.3,0.1

Type RM Length L Ch R = 1 ,12119   ,155,142.8,139.2
XS GIS Cut Line= 2
2042116.44513913309931.9634826752041739.20185842309397.866416828
#Sta/Elev= 30
       0 2476.96    33.9 2465.69    49.2 2458.65    59.5 2457.07      70 2451.96
    74.1  2451.1   184.6  2447.7   247.1 2447.78   264.2 2448.43   332.4 2447.24
   399.4 2448.69   415.5 2447.66   419.5 2447.93   432.9 2443.91   435.6 2444.14
   443.6 2447.56   470.6 2449.83   482.3 2448.57   507.9 2449.02     548 2451.81
   568.1 2454.03   572.1 2455.31   576.1  2457.9   580.2 2459.29   600.2  2460.5
   604.3 2461.49   612.3 2467.34   624.3 2473.66   632.4 2477.73   653.9 2487.14
#Mann= 6 ,-1 , 0
       0     .05       0  138.16     .07       0   419.5    .045       0
   443.6     .07       0  623.89     .06       0  631.46     .05       0
Bank Sta=419.5,443.6
XS Rating Curve= 0 ,0
Exp/Cntr(USF)=0,0
Exp/Cntr=0.5,0.3

Type RM Length L Ch R = 1 ,11976   ,70.5,88.4,84.6
XS GIS Cut Line= 2
  2042281.724379 309868.493511182041829.68667367309335.822076861
#Sta/Elev= 30
       0 2486.79    34.7 2479.27      79 2470.84   142.4 2457.69   155.3 2453.93
   191.9 2449.08   217.2 2447.19     273 2448.62   328.8    2447   379.2 2448.31
     392 2447.96   396.3 2446.71   400.6    2445   409.5 2443.99   426.4 2444.86
   439.3 2442.74   443.6 2443.64   447.9  2446.1   451.4 2446.92   458.4 2448.07
   503.8 2449.64   538.3 2452.51   559.8 2453.57   568.4 2457.41   572.7 2458.39
   607.4 2461.73   614.3 2464.32   646.9  2470.2   672.5 2477.04   698.6 2482.74
#Mann= 8 ,-1 , 0
       0     .05       0  276.63     .06       0  350.76     .07       0
   396.3    .045       0   451.4     .07       0  505.24    .055       0
  619.55     .05       0     673     .06       0
#XS Ineff= 2 , 0
          388.65    2448  454.59            2448
Permanent Ineff=
       F       F
Bank Sta=396.3,451.4
XS Rating Curve= 0 ,0
Exp/Cntr(USF)=0,0
Exp/Cntr=0.5,0.3

Type RM Length L Ch R = 1 ,11888   ,136.1,136.5,135.9
XS GIS Cut Line= 2
 2042352.4872765309836.3285577722041882.68114302309301.815764438
#Sta/Elev= 30
       0 2496.43      10 2494.09    21.9 2492.19    51.7 2481.13   136.4  2462.2
   180.3 2453.68   193.4 2449.47   210.9 2449.59     259 2447.91   328.9  2448.1
   352.6 2447.33   392.2 2447.55   407.5 2448.19   410.8 2447.54   420.6 2442.63
   422.4 2442.79   429.3 2445.74   439.3 2447.49     441 2447.79   449.3 2448.71
   494.8 2448.42   501.4 2449.04   513.9 2451.85   542.9 2452.66   582.2 2459.69
   633.2 2466.77     658 2471.04   667.9 2473.28   703.7 2478.08   711.6 2479.61
#Mann= 10 ,-1 , 0
       0     .05       0   10.68      .1       0  224.73     .05       0
   254.9     .06       0   410.8    .045       0   439.3     .06       0
     441     .06       0  486.01    .055       0  601.56      .1       0
  608.48     .05       0
Bank Sta=410.8,439.3
XS Rating Curve= 0 ,0
Exp/Cntr(USF)=0,0
Exp/Cntr=0.5,0.3

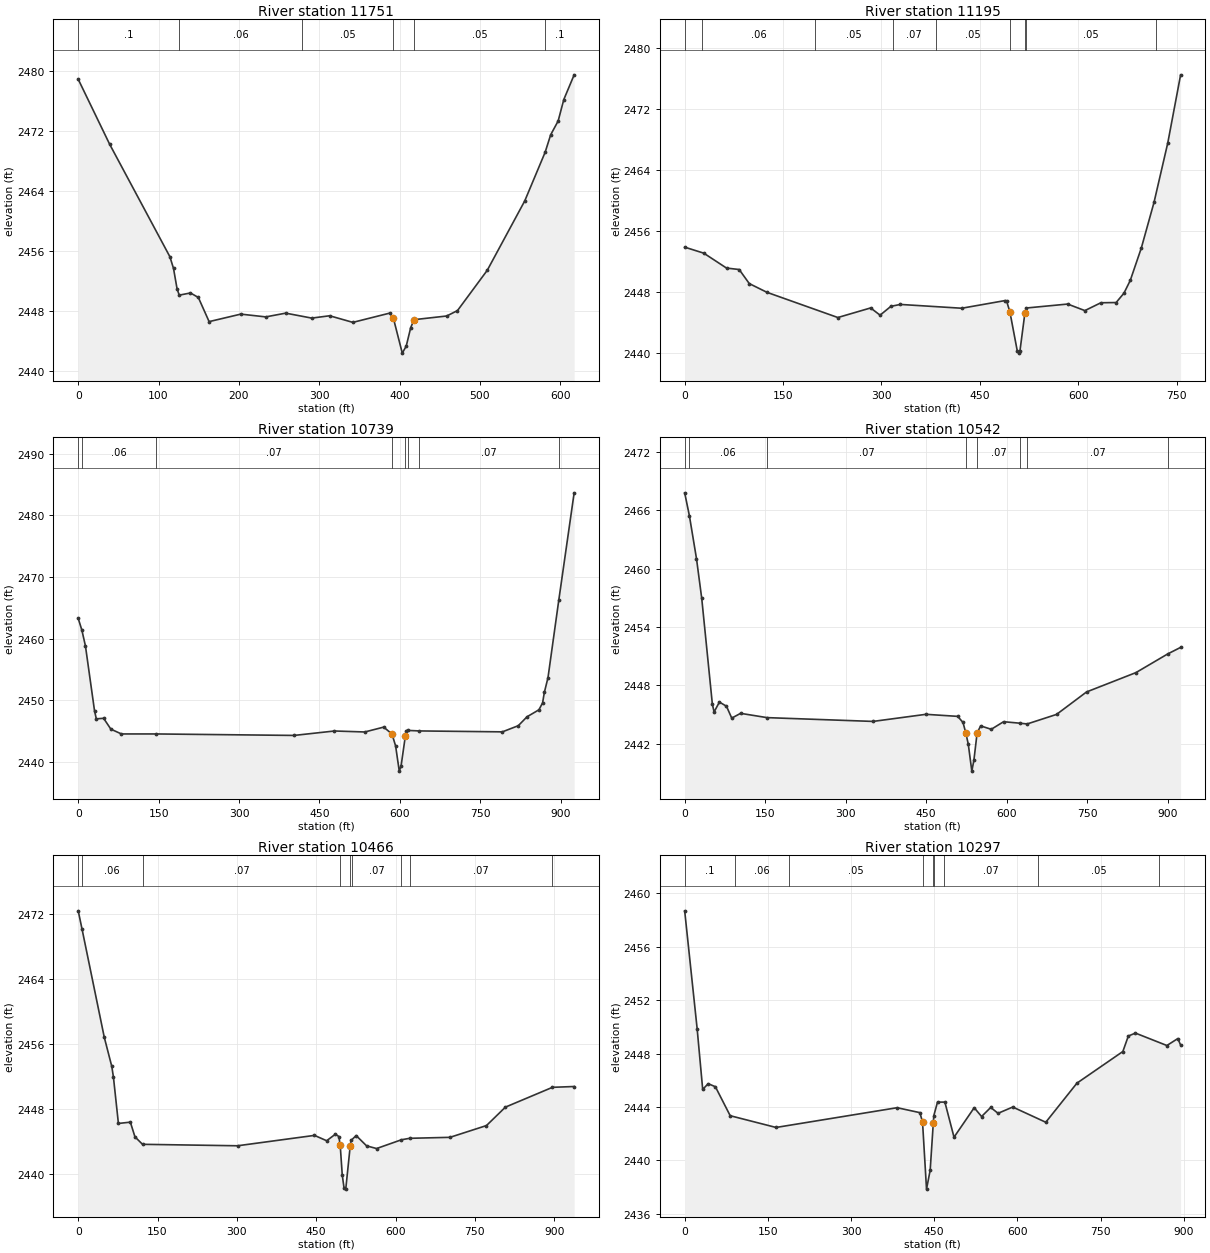
Type RM Length L Ch R = 1 ,11751   ,546.9,556.6,548.3
XS GIS Cut Line= 2
2042424.19623655309713.5594780542042011.21411872309254.911068349
#Sta/Elev= 30
       0 2478.84    39.1 2470.18   114.1 2455.18   118.6 2453.62     123 2450.92
   125.7 2450.06   139.7 2450.35   149.5 2449.75   162.9 2446.53   202.3 2447.53
   233.4 2447.16   258.2 2447.66   290.6    2447   312.9 2447.31   341.8 2446.43
   387.9 2447.67   392.3 2446.96   403.3 2442.33   408.2 2443.26   413.8 2445.73
     418 2446.79   458.6 2447.28     472    2448   509.1 2453.38   555.7 2462.62
   581.1 2469.11     588 2471.44   597.3 2473.28   604.3 2476.13   617.2 2479.43
#Mann= 6 ,-1 , 0
       0      .1       0  125.21     .06       0  278.97     .05       0
   392.3    .045       0     418     .05       0  580.69      .1       0
Bank Sta=392.3,418
XS Rating Curve= 0 ,0
Exp/Cntr(USF)=0,0
Exp/Cntr=0.3,0.1

Type RM Length L Ch R = 1 ,11195   ,441.1,455.6,451.2
XS GIS Cut Line= 2
2042821.62153041309623.9222240922042424.38435582308980.623155934
#Sta/Elev= 30
       0 2453.87    29.1 2453.08    63.8 2451.12    83.1 2450.93    98.5 2449.08
   125.5 2447.93   233.5 2444.62   283.5 2445.88   297.9 2444.93   314.4 2446.09
   328.8 2446.34   422.4 2445.84   488.6 2446.85   490.9 2446.75   495.8 2445.37
   507.2 2440.17     510 2439.94   511.1  2440.2   518.8 2445.28   520.8 2445.87
   583.9 2446.39   610.1 2445.53   634.5 2446.56   657.8 2446.59   669.7 2447.82
   679.3 2449.49   696.2 2453.76   715.5 2459.74   736.5 2467.56   756.1 2476.52
#Mann= 9 ,-1 , 0
       0     .05       0   27.13     .06       0  197.94     .05       0
  316.85     .07       0  382.74     .05       0   495.8    .045       0
   518.8     .05       0   520.8     .05       0  718.93      .1       0
Bank Sta=495.8,518.8
XS Rating Curve= 0 ,0
Exp/Cntr(USF)=0,0
Exp/Cntr=0.3,0.1

Type RM Length L Ch R = 1 ,10739   ,194.2,197.6,199.1
XS GIS Cut Line= 2
2043046.77620426309586.0390567452042819.83458855308688.994245036
#Sta/Elev= 30
       0 2463.29     6.8  2461.4    13.5 2458.82    30.5 2448.27    33.8    2447
    47.4 2447.09    60.9 2445.33    80.6 2444.55   145.9 2444.55   402.7 2444.31
   478.1 2445.03   534.7 2444.87     570 2445.66   585.5 2444.53   592.2  2442.6
     599 2438.52   602.4 2439.37   610.5 2444.29   612.5 2445.09   615.7 2445.12
   636.2 2445.04   791.4 2444.89   821.1 2445.89   837.3 2447.33   859.6 2448.47
   866.4 2449.59   869.7 2451.29   876.5 2453.69   896.6 2466.23   925.3 2483.66
#Mann= 8 ,-1 , 0
       0      .1       0     6.8     .06       0   145.9     .07       0
   585.5    .045       0   610.5     .07       0   615.7     .05       0
   636.2     .07       0   896.6      .1       0
Bank Sta=585.5,610.5
XS Rating Curve= 0 ,0
Exp/Cntr(USF)=0,0
Exp/Cntr=0.5,0.3

Type RM Length L Ch R = 1 ,10542   ,73.8,75.6,75.4
XS GIS Cut Line= 2
2043131.07255419 309565.288810772043064.17025036308643.523735842
#Sta/Elev= 30
       0 2467.78     8.8 2465.42      22 2461.02    31.8 2456.92    51.6 2446.05
    54.8 2445.25    64.7 2446.27    77.9 2445.84    87.7 2444.62   104.2 2445.11
   153.5 2444.67     351 2444.28   449.6 2445.01   508.8  2444.8   518.7 2444.17
   524.12443.045   528.5 2441.94   535.1 2439.17     539  2440.3     545 2443.11
   551.6 2443.82   571.3 2443.47   594.3 2444.25   624.1  2444.1   638.3 2444.02
     693    2445   748.9 2447.31     841  2449.3   900.2 2451.22   924.2 2451.89
#Mann= 8 ,-1 , 0
       0      .1       0     8.8     .06       0   153.5     .07       0
   524.1    .045       0     545     .07       0   624.1     .05       0
   638.3     .07       0   900.2      .1       0
Bank Sta=524.1,545
XS Rating Curve= 0 ,0
Exp/Cntr(USF)=0,0
Exp/Cntr=0.5,0.3

Type RM Length L Ch R = 1 ,10466   ,166.7,168.6,164.9
XS GIS Cut Line= 2
2043188.68287137309546.7048374852043142.22293816 308610.07258393
#Sta/Elev= 30
       0 2472.38     7.2 2470.14    49.3  2456.8    63.5 2453.21    66.6  2451.9
      76 2446.19    98.6 2446.35   107.3 2444.54   121.6 2443.62   301.3 2443.44
   446.8 2444.72   469.8 2444.06   486.4 2444.87   492.8 2444.58   495.4 2443.53
   499.3 2439.83   502.6 2438.28   505.9  2438.1   514.32443.372   515.8 2444.09
   525.6  2444.7   545.3 2443.43   564.2  2443.1   611.2 2444.18   626.8 2444.36
     703 2444.48     772 2445.93   807.8  2448.2   896.8 2450.64   937.8 2450.74
#Mann= 9 ,-1 , 0
       0      .1       0     7.2     .06       0   121.6     .07       0
   495.4    .045       0   514.3     .07       0   517.8     .07       0
   611.2     .05       0   626.8     .07       0   896.8      .1       0
Bank Sta=495.4,514.3
XS Rating Curve= 0 ,0
Exp/Cntr(USF)=0,0
Exp/Cntr=0.5,0.3

Type RM Length L Ch R = 1 ,10297   ,655.9,657.8,658.4
XS GIS Cut Line= 2
2043378.92632544309450.8926604172043262.00296943 308564.04003559
#Sta/Elev= 30
       0 2458.69    22.5 2449.85    32.5 2445.31    42.4 2445.74    55.4 2445.51
    82.1 2443.34   164.8 2442.46   383.2 2443.94   424.2 2443.57     429 2442.87
   436.2 2437.84   442.8 2439.26   448.42442.787   449.4 2443.35     456 2444.36
   469.3 2444.36   485.8 2441.73   522.2 2443.94   535.5 2443.28     552 2443.96
   565.2 2443.52   591.7 2443.99   651.3 2442.85   707.5 2445.78   790.3 2448.15
   800.2 2449.31     813 2449.53   869.7  2448.6   889.5 2449.12   894.5 2448.63
#Mann= 9 ,-1 , 0
       0      .1       0   89.99     .06       0  187.53     .05       0
     429    .045       0   448.4     .05       0   449.4     .05       0
  467.64     .07       0   637.1     .05       0   855.6      .1       0
Bank Sta=429,448.4
XS Rating Curve= 0 ,0
Exp/Cntr(USF)=0,0
Exp/Cntr=0.3,0.1

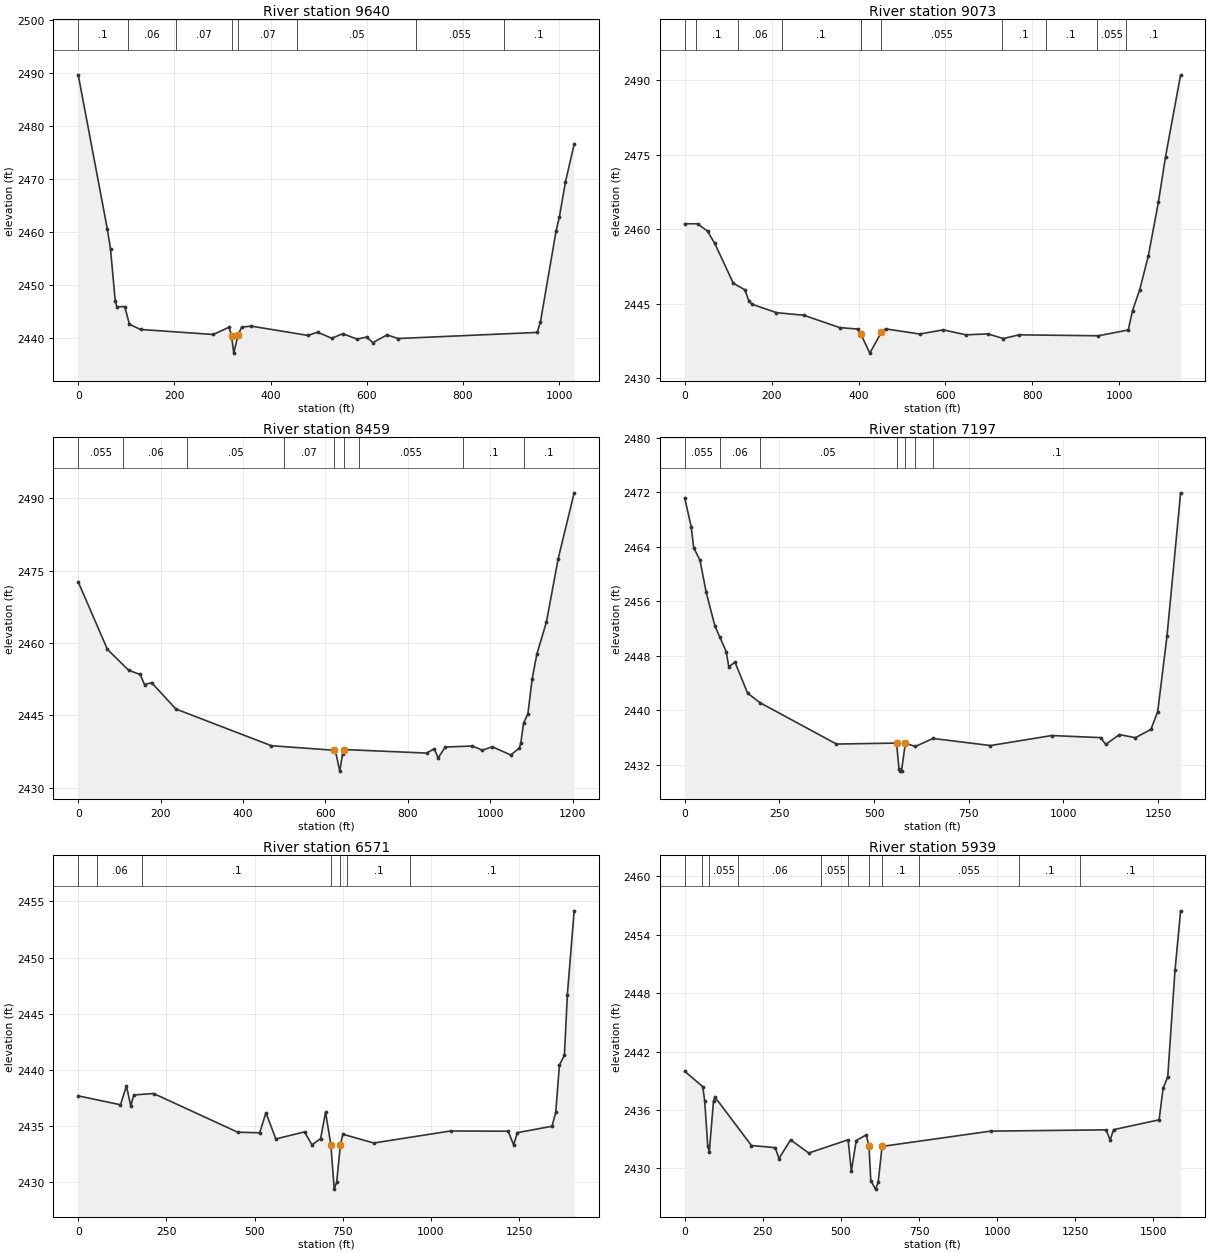
Type RM Length L Ch R = 1 ,9640    ,560.4,566.2,564
XS GIS Cut Line= 2
2043940.92817155309275.7747898292044003.19569673308246.285040106
#Sta/Elev= 30
       0  2489.6    60.6 2460.47    67.2 2456.67      77 2446.94    80.3 2445.81
    96.7 2445.85   106.6  2442.5   129.6 2441.53   280.8 2440.58   313.7 2441.95
   318.8 2440.33   323.5 2437.06   332.32440.467     340 2441.96   359.7 2442.16
     478  2440.4   497.7 2441.01   527.3 2439.87   550.3 2440.73   579.9  2439.7
   599.6 2440.09   612.8 2439.05   642.3  2440.5   665.4 2439.82   954.6 2440.97
   961.2 2442.92     994  2460.2  1000.7 2462.77  1013.1 2469.29  1031.4  2476.5
#Mann= 8 ,-1 , 0
       0      .1       0  103.45     .06       0  203.26     .07       0
   318.8    .045       0   332.3     .07       0  455.14     .05       0
  702.34    .055       0  885.03      .1       0
Bank Sta=318.8,332.3
XS Rating Curve= 0 ,0
Exp/Cntr(USF)=0,0
Exp/Cntr=0.3,0.1

Type RM Length L Ch R = 1 ,9073    ,596.8,614.5,600.8
XS GIS Cut Line= 2
 2044463.9753831 309408.612176892044596.81277016308275.343218526
#Sta/Elev= 30
       0 2461.13    29.6 2461.11    52.6 2459.62    69.1 2457.18     112 2449.15
   138.5 2447.84   147.6 2445.61     155 2444.94   211.1 2443.24   273.9 2442.72
   356.5 2440.24     399 2439.93   404.9    2439   425.9  2435.1   452.2 2439.25
   462.2 2439.98   540.9 2438.94   594.6 2439.78   647.2 2438.78   697.6 2438.97
   733.1 2438.03   769.4 2438.78   951.9 2438.59  1020.5 2439.76  1030.4 2443.67
  1046.9 2447.85  1066.7 2454.66  1089.8 2465.42  1106.3 2474.63    1141 2491.07
#Mann= 11 ,-1 , 0
       0     .12       0   26.48      .1       0  122.37     .06       0
  223.59      .1       0  404.71    .055       0   404.9    .045       0
   452.2    .055       0  729.68      .1       0   830.9      .1       0
  947.48    .055       0 1016.26      .1       0
Bank Sta=404.9,452.2
XS Rating Curve= 0 ,0
Exp/Cntr(USF)=0,0
Exp/Cntr=0.3,0.1

Type RM Length L Ch R = 1 ,8459    ,1224.8,1262,1223.7
XS GIS Cut Line= 2
2044903.99922774309636.9264359012045285.90671554308495.355140845
#Sta/Elev= 30
       0 2472.64      71 2458.66   122.8 2454.34   150.5 2453.48   160.9 2451.39
   178.2 2451.79     237 2446.34   468.8 2438.74     621  2437.8   624.5 2437.58
   634.9 2433.48   641.8  2437.1   645.2 2437.95   845.4 2437.22   864.3  2438.1
   873.6 2436.19   890.9 2438.47   956.6 2438.68   980.9 2437.82    1005 2438.52
    1050 2436.83  1070.8 2438.25  1074.3 2439.29  1081.1 2443.44  1091.5 2445.32
  1101.9 2452.59  1113.1 2457.64  1136.5 2464.34    1165 2477.43  1203.8 2491.08
#Mann= 9 ,-1 , 0
       0    .055       0  109.37     .06       0  265.21     .05       0
  499.25     .07       0     621    .045       0   645.2     .07       0
   682.7    .055       0  934.31      .1       0 1082.57      .1       0
Bank Sta=621,645.2
XS Rating Curve= 0 ,0
Exp/Cntr(USF)=0,0
Exp/Cntr=0.3,0.1

Type RM Length L Ch R = 1 ,7197    ,626,625.4,619.1
XS GIS Cut Line= 2
 2046037.2681861309757.3103179252045875.37262062308457.994625735
#Sta/Elev= 30
       0 2471.19    17.2 2466.95    23.8 2463.86    40.3 2462.06    56.9 2457.29
      80 2452.34    93.3 2450.68   109.8 2448.58   116.4 2446.38   132.9 2447.05
     166 2442.51   198.9  2441.1   400.7 2435.03   559.4 2435.17     566 2431.32
   569.6 2431.05   572.6 2431.13   582.6 2435.16     609 2434.67   655.3 2435.85
   807.4 2434.81   969.4 2436.28  1098.3 2435.97  1111.6 2434.97  1147.9 2436.42
  1189.9 2435.96    1231 2437.18  1248.9  2439.8  1273.6 2450.97  1309.4 2471.93
#Mann= 7 ,-1 , 0
       0    .055       0    93.3     .06       0   198.9     .05       0
   559.4    .045       0   582.6     .05       0     609      .1       0
   655.3      .1       0
Bank Sta=559.4,582.6
XS Rating Curve= 0 ,0
Exp/Cntr(USF)=0,0
Exp/Cntr=0.3,0.1

Type RM Length L Ch R = 1 ,6571    ,579.1,632.8,579.8
XS GIS Cut Line= 3
2046869.71282838309766.6368865492046745.24922686309604.856142385
2046318.89568541308480.727544009
#Sta/Elev= 30
       0  2437.7   119.8 2436.91   136.8 2438.58   149.2 2436.79   157.4 2437.78
   213.7 2437.91   452.3 2434.47   514.6 2434.42   532.4  2436.2   560.4 2433.87
   641.8  2434.5   662.8 2433.35   687.4  2433.9   701.4 2436.26   716.42433.363
     726 2429.41     733 2430.02   743.5 2433.36   750.6 2434.29   838.3 2433.51
  1055.8 2434.58  1219.3 2434.56  1234.8 2433.34  1245.3 2434.43  1343.6    2435
  1354.2 2436.23  1364.6 2440.44  1378.7 2441.31  1387.2 2446.71  1406.4 2454.15
#Mann= 7 ,-1 , 0
       0    .055       0   53.56     .06       0  182.18      .1       0
   716.4    .045       0   743.5      .1       0  763.58      .1       0
  941.27      .1       0
Bank Sta=716.4,743.5
XS Rating Curve= 0 ,0
Exp/Cntr(USF)=0,0
Exp/Cntr=0.5,0.3

Type RM Length L Ch R = 1 ,5939    ,465,504.4,485.8
XS GIS Cut Line= 3
2047375.13176428309670.092505631 2047024.8149256309292.570562386
2046345.73883008308463.186414827
#Sta/Elev= 30
       0 2439.99    57.9 2438.41    64.2  2436.9    73.8 2432.32    78.7  2431.7
    92.3 2436.97    96.8 2437.34   213.7 2432.36     290 2432.14   301.6 2431.02
   338.8 2432.94     397 2431.59     523 2432.95   533.3 2429.72   548.9 2432.87
     581 2433.46   589.8 2432.26   595.5 2428.76   610.6 2427.88   619.1 2428.58
   631.7 2432.27   979.2 2433.84  1348.4 2433.97  1361.5 2432.91  1372.3 2433.99
  1518.1    2435  1530.8 2438.24  1545.7 2439.42  1568.9 2450.35  1586.9 2456.47
#Mann= 11 ,-1 , 0
       0     .06       0      54    .055       0   77.86    .055       0
  171.61     .06       0  436.46    .055       0  524.09      .1       0
   589.8    .045       0   631.7      .1       0  750.31    .055       0
 1070.67      .1       0 1264.97      .1       0
#XS Ineff= 2 , 0
          579.46    2432  649.88            2432
Permanent Ineff=
       F       F
Bank Sta=589.8,631.7
XS Rating Curve= 0 ,0
Exp/Cntr(USF)=0,0
Exp/Cntr=0.5,0.3