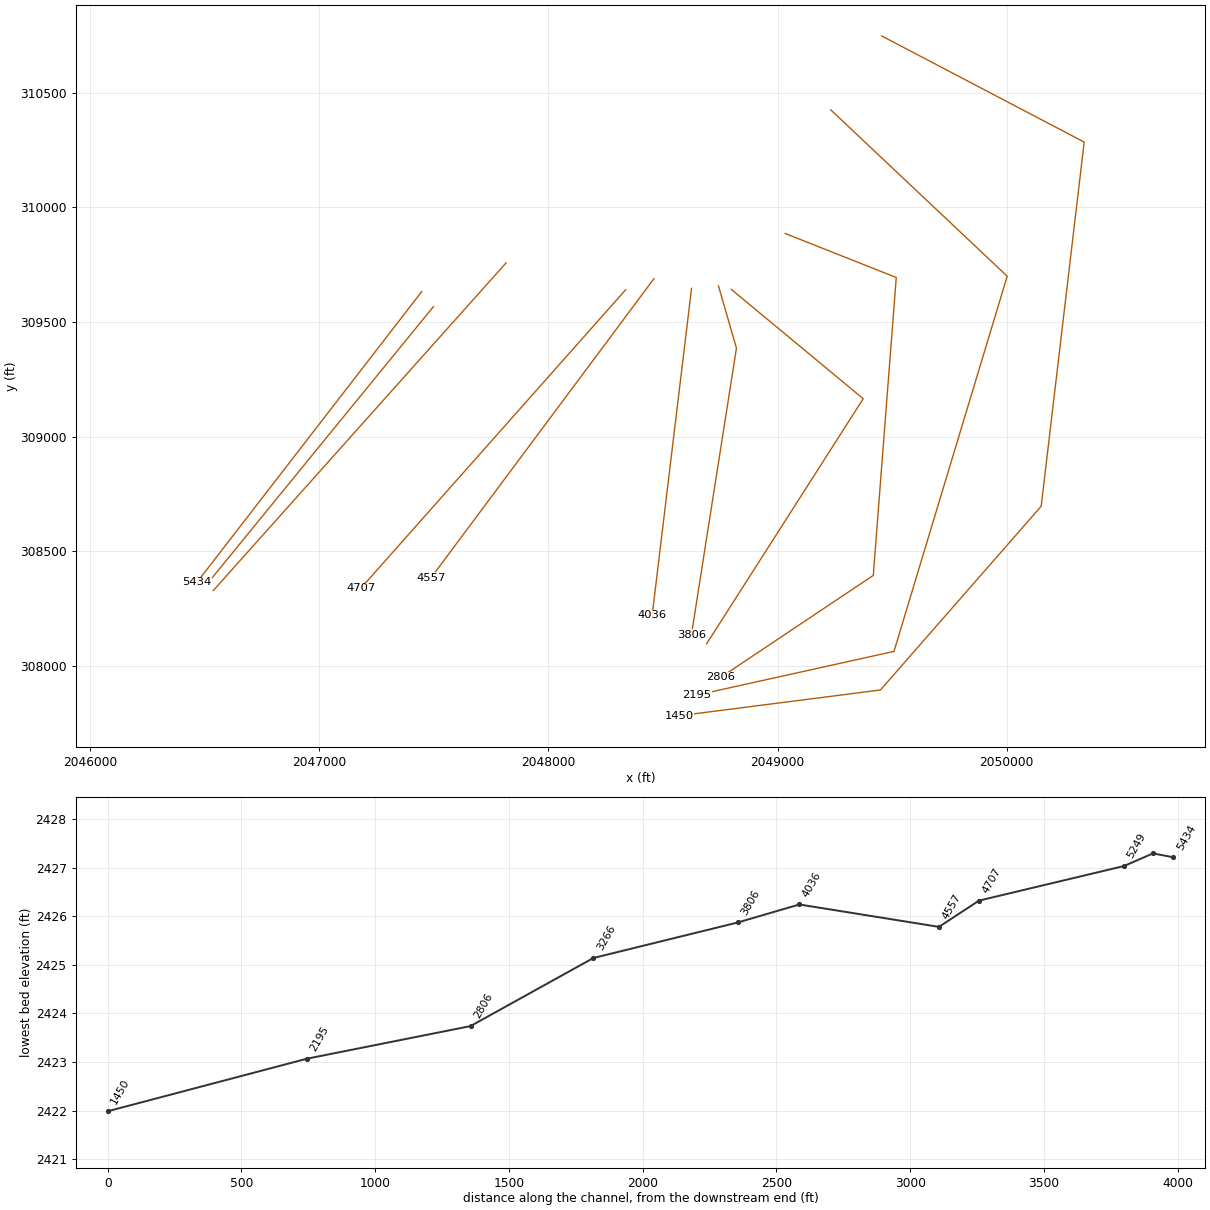
HEC-RAS study MORRISFK.prj: MORRISFK

--- MORRISFK.g02 (geometry) --- (continued)

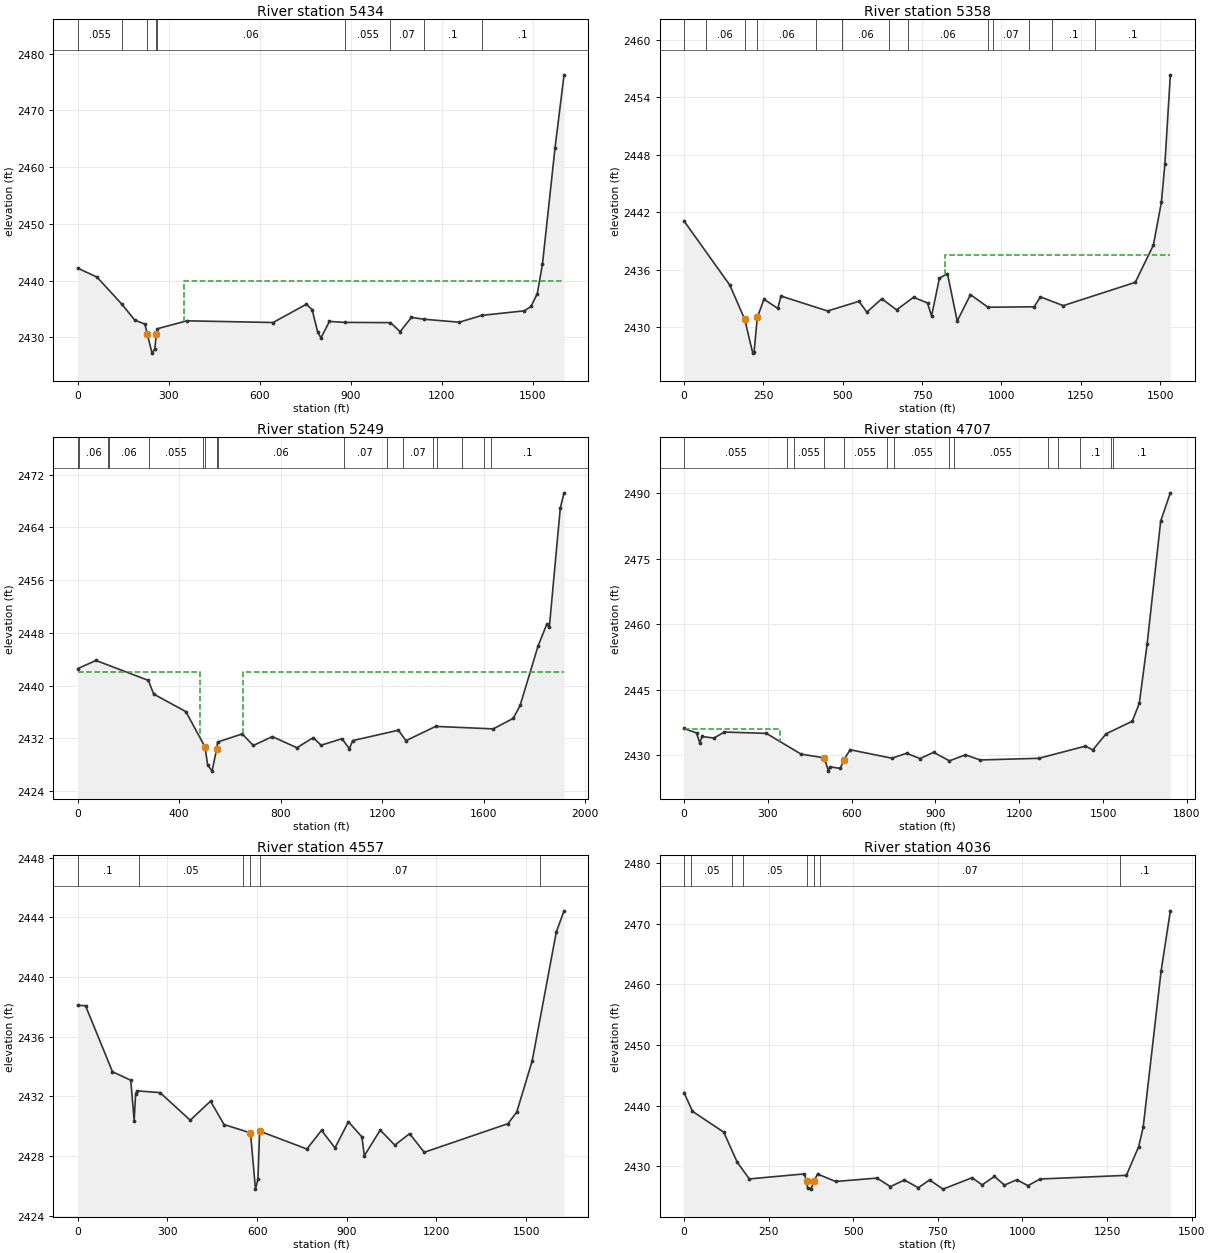
Type RM Length L Ch R = 1 ,5434    ,77.8,76.5,75.3
XS GIS Cut Line= 2
2047447.80886911  309632.91021962046467.31951054308364.647234291
#Sta/Elev= 30
       0 2442.19    63.4 2440.62   144.4 2435.91   187.8 2433.04   221.6 2432.32
   229.3 2430.55     245 2427.21   254.1 2427.95     259 2430.59   262.4 2431.51
   359.6 2432.91     644 2432.61   753.5 2435.83   772.5 2434.89     791 2430.92
   801.7 2429.91   829.7  2432.8   881.1 2432.63  1030.8 2432.59  1062.8    2431
  1100.1 2433.52  1140.8 2433.19  1257.7 2432.66  1332.4 2433.87  1472.2 2434.67
  1494.1 2435.45  1514.8 2437.68    1532 2442.94  1573.4 2463.42  1603.1 2476.29
#Mann= 9 ,-1 , 0
       0    .055       0   144.4     .06       0   229.3    .045       0
     259     .06       0   262.4     .06       0   881.1    .055       0
  1030.8     .07       0  1140.8      .1       0  1332.4      .1       0
#XS Ineff= 2 , 0
                             350            2440
Permanent Ineff=
       F       F
Bank Sta=229.3,259
XS Rating Curve= 0 ,0
Exp/Cntr(USF)=0,0
Exp/Cntr=0.5,0.3

Type RM Length L Ch R = 1 ,5358    ,109.5,108.7,105.7
XS GIS Cut Line= 2
2047498.44154233309566.766582028 2046529.9631784 308379.88421348
#Sta/Elev= 30
       0 2441.09   144.5 2434.38   191.3 2430.81   216.5 2427.29   220.7 2427.44
   230.9 2431.02   251.9 2432.92   295.3 2431.96   305.4 2433.25   452.4 2431.69
     551  2432.7     576 2431.57     623 2432.97   669.6 2431.81   722.9 2433.12
     767 2432.53   779.7 2431.16   804.5 2435.11   829.8  2435.6   860.5 2430.64
   902.4  2433.4   957.5 2432.08    1103 2432.13  1122.7 2433.16  1194.7 2432.25
  1421.4 2434.68  1478.4 2438.56    1504  2443.1  1514.8 2447.09  1531.9 2456.35
#Mann= 13 ,-1 , 0
       0    .055       0   68.59     .06       0   191.3    .045       0
   230.9     .06       0  414.98     .07       0  498.87     .06       0
  644.86     .07       0  704.32     .06       0   958.9    .055       0
  972.58     .07       0 1085.58      .1       0 1157.58      .1       0
 1295.72      .1       0
#XS Ineff= 2 , 0
                          821.28         2437.58
Permanent Ineff=
       F       F
Bank Sta=191.3,230.9
XS Rating Curve= 0 ,0
Exp/Cntr(USF)=0,0
Exp/Cntr=0.5,0.3

Type RM Length L Ch R = 1 ,5249    ,550.6,541.6,533.3
XS GIS Cut Line= 2
 2047815.5631167309757.7870750492046538.23060483308328.233590256
#Sta/Elev= 30
       0 2442.59    71.9 2443.82   278.5  2440.8   299.5 2438.72   426.2 2436.06
   502.12430.675   511.9 2427.99   529.5 2427.03   547.52430.366   551.5 2431.44
   648.3 2432.68   692.2 2430.92   767.1 2432.27   863.9 2430.58   928.4 2432.11
   959.4 2430.96  1041.7 2431.95  1070.7 2430.44  1083.9 2431.66  1264.2 2433.24
    1294 2431.65    1411 2433.82  1637.9 2433.44  1716.9 2435.04  1743.8 2436.99
  1814.2 2445.96  1849.2 2449.34  1859.1 2448.89  1902.2 2466.93  1917.1 2469.26
#Mann= 17 ,-1 , 0
       0    .055       0    5.07     .06       0  121.24    .055       0
  123.56     .06       0  282.06    .055       0  492.66     .06       0
   502.1    .045       0   547.5     .06       0   551.5     .06       0
  1048.1     .07       0  1218.8     .06       0 1282.86     .07       0
 1399.02    .055       0 1415.41      .1       0 1515.18    .055       0
 1599.95      .1       0 1627.81      .1       0
#XS Ineff= 2 , 0
          480.31    2442  650.19            2442
Permanent Ineff=
       F       F
Bank Sta=502.1,547.5
XS Rating Curve= 0 ,0
Exp/Cntr(USF)=0,0
Exp/Cntr=0.5,0.3

Type RM Length L Ch R = 1 ,4707    ,124.1,149.9,155.1
XS GIS Cut Line= 2
2048337.34290158309640.7341749452047181.96625029308338.383976573
#Sta/Elev= 30
       0  2436.1    44.8 2435.07    56.4 2432.79    64.3 2434.26   106.8  2433.9
   144.7 2435.28   294.6 2434.98   418.9 2430.22   502.2 2429.36   517.1 2426.32
     522 2427.32   559.9 2426.93   571.5 2428.87     595 2431.22   744.1 2429.28
   796.8 2430.42     845 2429.19   893.3 2430.63   950.3 2428.68  1007.3 2430.06
  1059.9 2428.88  1270.4 2429.26  1437.1 2432.06  1463.4 2431.18  1511.2 2434.89
  1604.7 2437.75  1629.8 2441.86  1657.7 2455.37  1706.5 2483.66    1741 2490.12
#Mann= 14 ,-1 , 0
       0    .055       0     370    .055       0  393.71    .055       0
   502.2    .045       0   571.5    .055       0  727.18     .07       0
  752.33    .055       0  947.88      .1       0  967.46    .055       0
 1302.67     .05       0 1338.99    .055       0 1416.29      .1       0
 1529.91    .055       0 1534.55      .1       0
#XS Ineff= 2 , 0
          344.31 2436.09
Permanent Ineff=
       F       F
Bank Sta=502.2,571.5
XS Rating Curve= 0 ,0
Exp/Cntr(USF)=0,0
Exp/Cntr=0.5,0.3

Type RM Length L Ch R = 1 ,4557    ,505.9,521.9,528
XS GIS Cut Line= 2
2048460.65566869  309688.89197882047488.33705477308384.296415594
#Sta/Elev= 30
       0  2438.1      26 2438.08   116.3 2433.65   177.4 2433.08   188.8 2430.38
   193.7 2432.16   198.2 2432.37   275.5 2432.25   376.4  2430.4   444.3 2431.68
   489.6 2430.11     578 2429.55   594.7 2425.78   602.9 2426.45   608.5 2429.67
   766.6 2428.47   815.7 2429.72   860.7 2428.55   905.7  2430.3   950.8 2429.28
   958.9 2428.02  1012.1 2429.74  1060.9 2428.73  1110.3  2429.5  1159.4 2428.25
  1439.4 2430.17  1468.9 2430.95  1520.5 2434.38  1601.3 2443.03  1627.1 2444.44
#Mann= 6 ,-1 , 0
       0      .1       0  203.79     .05       0  552.17     .07       0
     578    .045       0   608.5     .07       0    1548     .06       0
Bank Sta=578,608.5
XS Rating Curve= 0 ,0
Exp/Cntr(USF)=0,0
Exp/Cntr=0.3,0.1

Type RM Length L Ch R = 1 ,4036    ,231.1,230.3,228.4
XS GIS Cut Line= 2
 2048624.7803435309646.9226891122048452.94773986 308220.19137406
#Sta/Elev= 30
       0 2442.15      25 2439.06   117.5 2435.62   157.2 2430.68   192.9 2427.92
   355.4 2428.75   362.1 2427.56   365.3 2426.36   375.3 2426.33   384.5  2427.6
   394.5 2428.73     448  2427.5   570.2 2428.06   609.8 2426.66   651.1 2427.74
   692.5 2426.47   725.5 2427.76   765.2 2426.24   851.1 2428.12   880.8 2426.94
   917.2 2428.33   946.9 2426.91   983.3 2427.78  1016.3 2426.82  1052.2 2427.91
  1307.1 2428.51  1343.5 2433.26  1356.7 2436.42  1409.6 2462.14    1437  2472.1
#Mann= 8 ,-1 , 0
       0     .06       0   19.43     .05       0  142.99      .1       0
  175.49     .05       0   362.1    .045       0   384.5     .05       0
  402.65     .07       0 1287.87      .1       0
Bank Sta=362.1,384.5
XS Rating Curve= 0 ,0
Exp/Cntr(USF)=0,0
Exp/Cntr=0.3,0.1

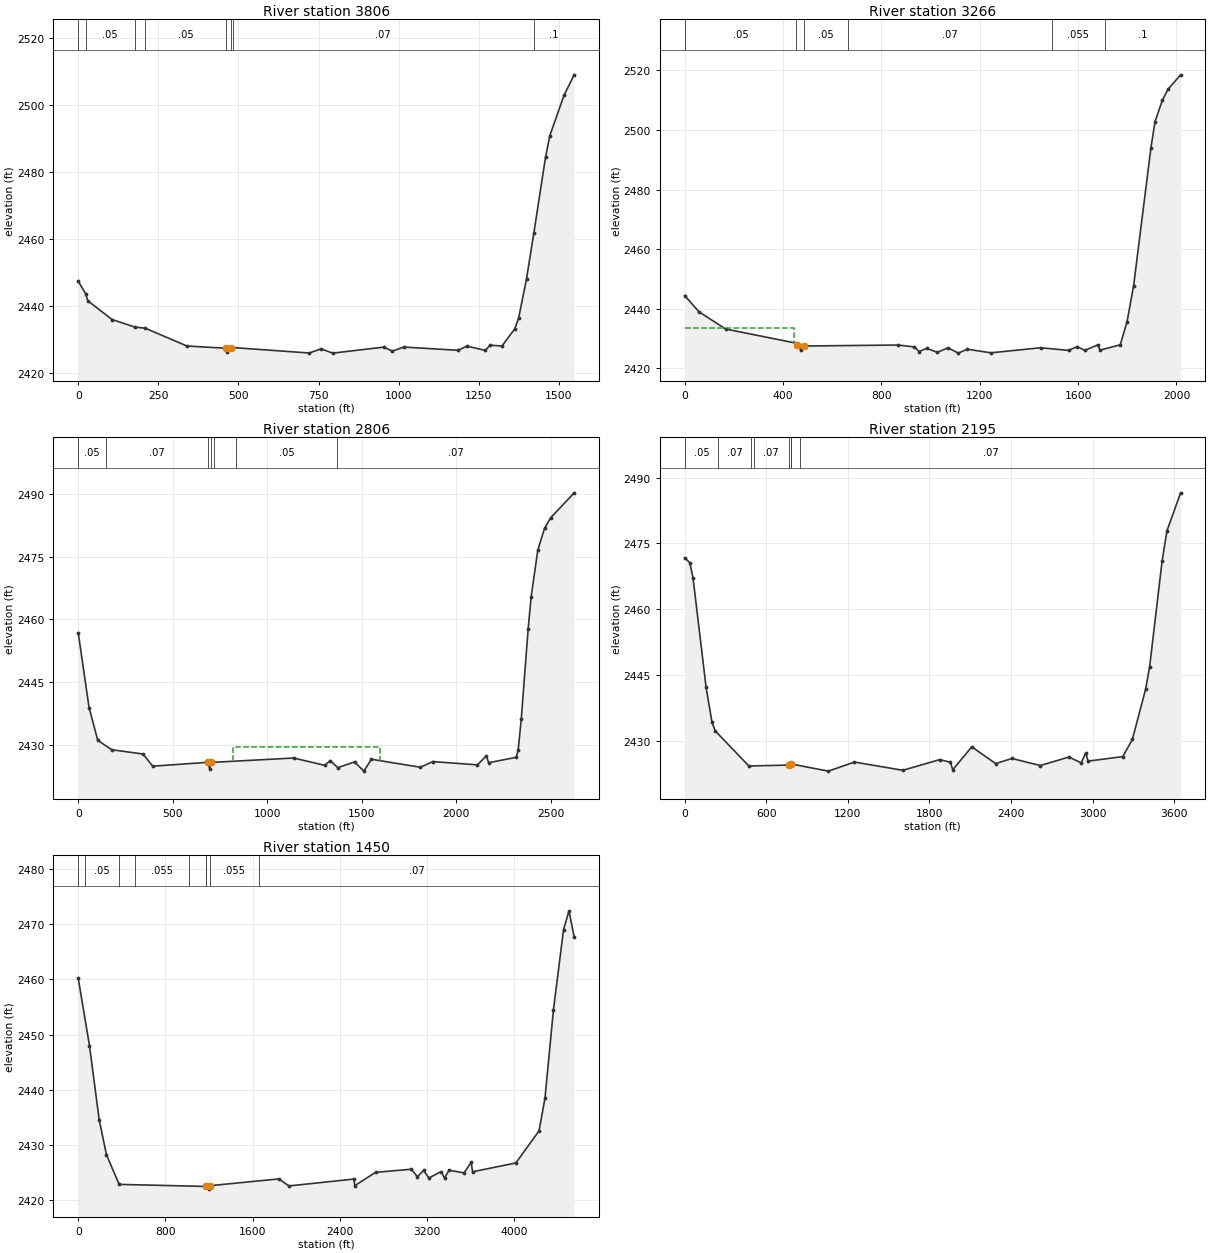
Type RM Length L Ch R = 1 ,3806    ,531.4,539.8,542.1
XS GIS Cut Line= 3
 2048742.1314728309657.5492913772048820.64601574309386.019830385
 2048624.3596584308136.330021963
#Sta/Elev= 30
       0 2447.33    23.2 2443.59      30 2441.49   105.5  2435.9   176.9 2433.63
   208.8 2433.32   339.2    2428   460.12427.331   465.4 2426.24   475.92427.398
     482 2427.53   721.1 2425.91   757.7 2427.14   794.2 2425.87   953.6 2427.66
   980.2 2426.47  1016.7 2427.68  1186.1 2426.71  1212.7 2427.97  1269.8 2426.69
  1285.7 2428.24  1322.3 2427.99  1362.1 2433.08  1374.5 2436.34    1399 2448.02
    1422 2461.74  1458.4  2484.3  1471.7 2490.74  1516.3 2502.83  1547.7 2508.89
#Mann= 8 ,-1 , 0
       0     .06       0    23.2     .05       0   176.9      .1       0
   208.8     .05       0   460.1    .045       0   475.9     .05       0
     482     .07       0    1422      .1       0
Bank Sta=460.1,475.9
XS Rating Curve= 0 ,0
Exp/Cntr(USF)=0,0
Exp/Cntr=0.3,0.1

Type RM Length L Ch R = 1 ,3266    ,467.4,459.4,452.1
XS GIS Cut Line= 3
2048797.64746775309642.7387334532049373.70233639309165.269147153
2048690.60917793308096.301136943
#Sta/Elev= 30
       0 2444.44      58    2439   166.3 2433.23   452.9 2428.49   455.3 2428.02
   473.9 2426.06   484.7 2427.52   867.9 2427.86   934.1 2427.22   953.6 2425.68
   984.7 2426.76  1027.6 2425.39  1070.4 2426.92  1113.2 2425.14  1148.3 2426.46
  1245.6 2425.25  1447.1 2426.94  1561.2 2426.06    1596 2427.33  1627.7 2426.07
  1679.9 2427.91  1689.5 2426.16  1771.2 2427.92  1799.1 2435.69  1825.7 2447.75
  1895.8 2493.81  1912.7 2502.76  1942.5 2509.94  1965.9 2513.67  2016.8 2518.46
#Mann= 6 ,-1 , 0
       0     .05       0   452.9    .045       0   484.7     .05       0
  664.19     .07       0 1492.66    .055       0 1709.02      .1       0
#XS Ineff= 2 , 0
          444.02 2433.49
Permanent Ineff=
       F       F
Bank Sta=455.3,484.7
XS Rating Curve= 0 ,0
Exp/Cntr(USF)=0,0
Exp/Cntr=0.3,0.1

Type RM Length L Ch R = 1 ,2806    ,549.8,611.4,656
XS GIS Cut Line= 4
2049033.21525125309886.2683366922049517.84531214 309694.13249135
2049417.58715172 308394.379874842048753.02917815   307950.378077
#Sta/Elev= 30
       0 2456.84    57.5 2438.91   103.4  2431.1   177.5 2428.85   343.4 2427.83
   393.8 2424.92   684.3 2425.84   695.6 2424.34   702.7 2425.82  1139.8 2426.87
  1304.5 2425.13  1333.9 2426.27  1373.4 2424.57  1462.3 2425.93  1511.6 2423.74
  1551.1 2426.58  1811.1 2424.66  1876.1 2426.02  2112.4 2425.24  2159.7 2427.39
  2171.8 2425.75  2317.6 2427.04  2327.9  2428.7  2344.5 2436.23  2380.7 2457.65
  2396.5 2465.35  2431.9 2476.57  2467.5 2481.75  2499.1 2484.24  2624.2 2490.25
#Mann= 7 ,-1 , 0
       0     .05       0  147.43     .07       0   684.3    .045       0
   702.7     .07       0   717.7     .07       0  835.43     .05       0
 1368.68     .07       0
#XS Ineff= 1 ,-1
  818.56  1598.4 2429.45
Permanent Ineff=
       F
Bank Sta=684.3,702.7
XS Rating Curve= 0 ,0
Exp/Cntr(USF)=0,0
Exp/Cntr=0.3,0.1

Type RM Length L Ch R = 1 ,2195    ,744.8,744.8,744.8
XS GIS Cut Line= 4
2049231.91157068310425.7025425322050001.83601316309699.694062181
2049507.88359411308062.9546416162048648.39707987307872.663511569
#Sta/Elev= 30
       0 2471.71    37.9 2470.61    61.9 2467.02   157.5 2442.18   200.5 2434.28
   224.4 2432.25   472.3 2424.24   765.4 2424.45   783.7  2424.7  1056.5 2423.07
  1248.9 2425.13  1605.3 2423.26  1876.5  2425.7  1954.9 2425.09    1972 2423.39
  2112.1 2428.61  2287.3 2424.79  2407.2 2425.95  2616.3 2424.35  2826.3 2426.28
  2916.8 2424.96  2950.6 2427.24  2967.4 2425.35  3222.8 2426.38  3293.4 2430.31
  3390.8 2441.76  3420.3 2446.89  3511.8 2470.92  3547.4 2477.83  3648.2 2486.53
#Mann= 8 ,-1 , 0
       0     .05       0  246.34     .07       0  485.15    .055       0
  507.79     .07       0   765.4    .045       0   783.7     .07       0
   784.5     .07       0   848.8     .07       0
Bank Sta=765.4,783.7
XS Rating Curve= 0 ,0
Exp/Cntr(USF)=0,0
Exp/Cntr=0.3,0.1

Type RM Length L Ch R = 1 ,1450    ,,,
XS GIS Cut Line= 5
2049454.47529478310747.9079972252050337.70277131310284.881987683
2050150.09334756308696.1719528042049448.79084469307894.620332602
2048570.26261587307782.192026938
#Sta/Elev= 30
       0 2460.22   103.4 2447.99   192.3 2434.56   258.9 2428.23   375.5 2422.85
  1171.82422.476  1195.5 2421.99  1205.4 2422.61  1840.2 2423.84  1932.2 2422.57
  2526.8 2423.81  2536.8 2422.63  2726.8 2425.03  3054.8  2425.6  3110.6 2424.22
    3167 2425.39  3215.2    2424  3328.3 2425.18  3358.9 2424.01  3401.2 2425.42
  3537.6 2424.93    3604 2426.85  3616.1 2425.14  4013.4 2426.73  4225.5 2432.55
  4280.2 2438.47  4357.8  2454.5  4450.6 2469.03    4500 2472.43  4547.7 2467.74
#Mann= 9 ,-1 , 0
       0     .06       0    59.3     .05       0  372.35     .07       0
  519.11    .055       0  1012.3    .055       0 1169.06     .07       0
  1171.8    .045       0  1205.4    .055       0 1658.81     .07       0
Bank Sta=1171.8,1205.4
XS Rating Curve= 0 ,0
Exp/Cntr(USF)=0,0
Exp/Cntr=0.3,0.1
LCMann Table=0

Chan Stop Cuts=-1
Use User Specified Reach Order=0
Composite Channel Slope=5